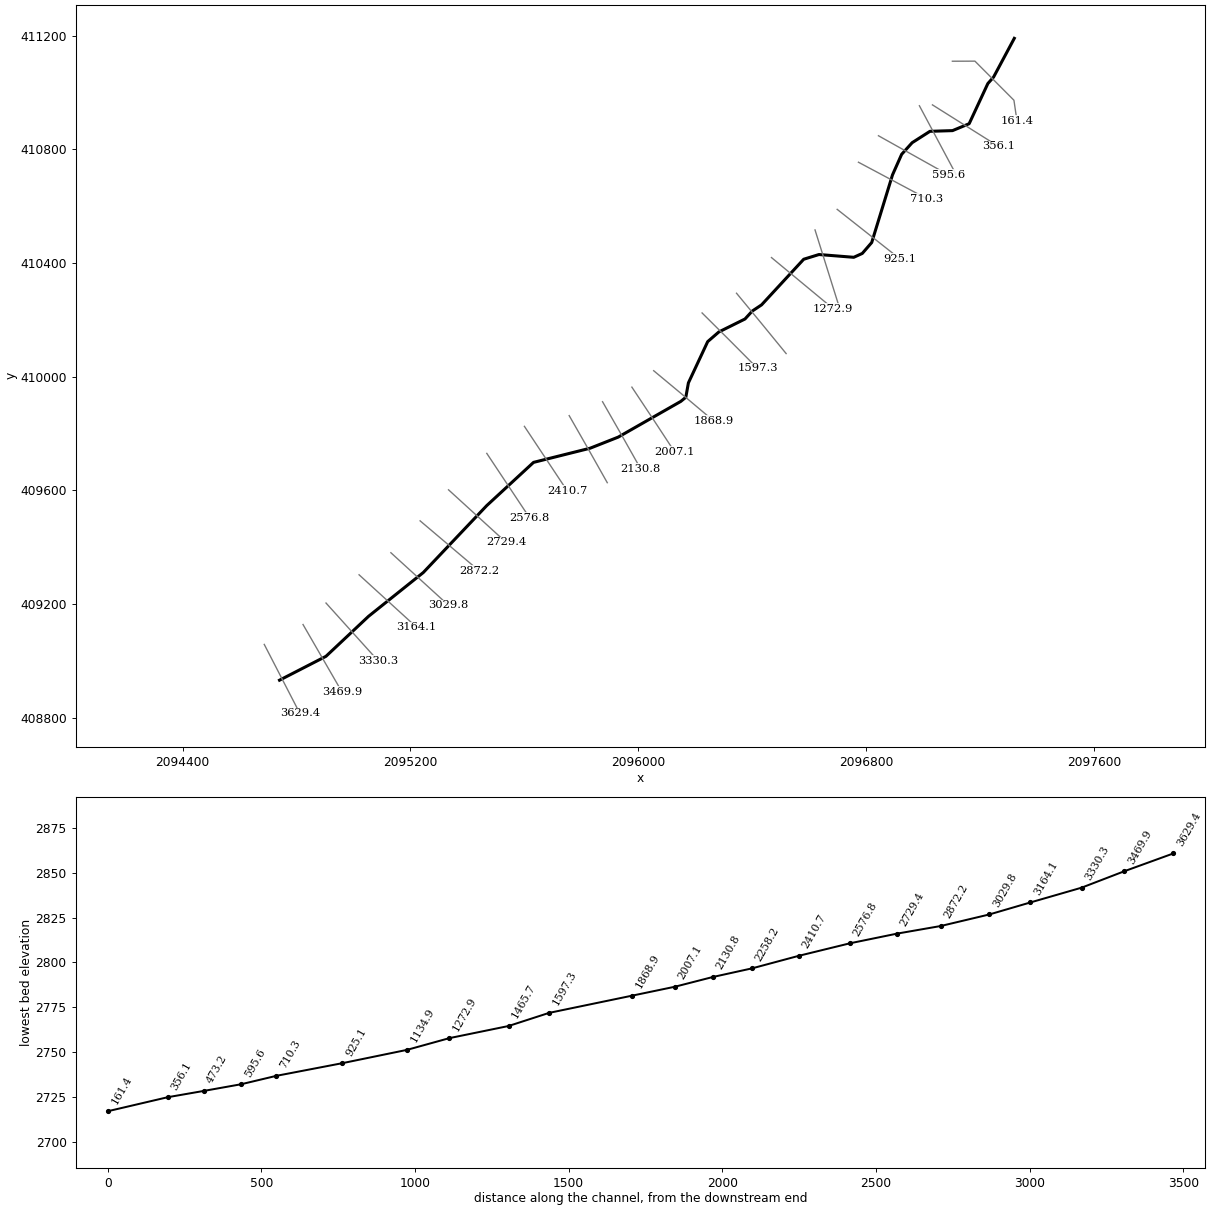
--- HogcampRun.prj (project) ---

Proj Title=HogcampRun
Current Plan=p01
Geom File=g01
Flow File=f01
Plan File=p01
DSS Export Rating Curves=0
DSS Export Rating Curve Sorted=0
DSS Export Volume Flow Curves=0
DXF OffsetX=0
DXF OffsetY=0
DXF ScaleX=0
DXF ScaleY=0

--- HogcampRun.p01 (plan) ---

Plan Title=Floodplain
Program Version=4.00
Geom File=g01
Flow File=f01
K Sum by GR=0
Std Step Tol=0.01
Critical Tol=0.01
Num of Std Step Trials=20
Max Error Tol=0.3
Flow Tol Ratio=0.001
Split Flow NTrial=30
Split Flow Tol=0.02
Split Flow Ratio=0.02
Log Output Level=0
Friction Slope Method=1
Unsteady Friction Slope Method=2
Unsteady Bridges Friction Slope Method=1
Global Log Level=0
CheckData=False
Run HTab=0
Run UNet=0
Run PostProcess=0
UNET Theta=0
UNET Theta Warmup=0
UNET ZTol=0
UNET ZSATol=0
UNET MxIter=0
UNET MaxInSteps=0
UNET DtIC=0
UNET DtMin=0
UNET MaxCRTS=0
UNET WFStab=0
UNET SFStab=0
UNET WFX=0
UNET SFX=0
UNET DSS MLevel=0
UNET DZMax Abort=0
UNET Convert EG Bridges=0
UNET Use Existing IB Tables=0
UNET Froude Limit=0
UNET Froude Power=0
Write IC File=0
Echo Input=False
Echo Output=False
Write Detailed=0

--- HogcampRun.f01 (steady flow) ---

Flow Title=NFF Regression Equation
Program Version=4.00
Number of Profiles=1
Profile Names=P100yr
River Rch & RM=HogcampRun,Main      ,3629.4
551.9811
River Rch & RM=HogcampRun,Main      ,3164.1
554.0152
River Rch & RM=HogcampRun,Main      ,2258.2
614.2113
River Rch & RM=HogcampRun,Main      ,161.4
637.8743
Boundary for River Rch & Prof#=HogcampRun,Main      ,1
Up Type=0
Dn Type=3
Dn Slope=0.03256

--- HogcampRun.g01 (geometry) ---

Geom Title=USGS 10m DEM
Program Version=4.00

River Reach=HogcampRun     ,Main
Reach XY= 30
     2094740.225      408931.972     2094903.311      409015.956
     2095052.811      409156.715     2095245.108      409310.878
     2095467.764      409546.230     2095632.291      409698.517
     2095831.045      409748.378     2095929.678      409787.440
     2096149.564      409913.222     2096167.086      409927.652
     2096176.131      409978.235     2096243.874      410123.486
     2096283.041      410157.499     2096374.860      410203.119
     2096400.337      410231.023     2096433.095      410252.861
     2096581.055      410413.397     2096634.756      410430.019
     2096756.826      410420.253     2096786.768      410433.863
     2096819.891      410472.236     2096892.908      410710.248
     2096925.098      410782.788     2096961.904      410823.573
     2097024.405      410863.612     2097103.691      410866.071
     2097162.104      410890.369     2097227.759      411031.753
     2097247.917      411054.564     2097320.647      411190.853

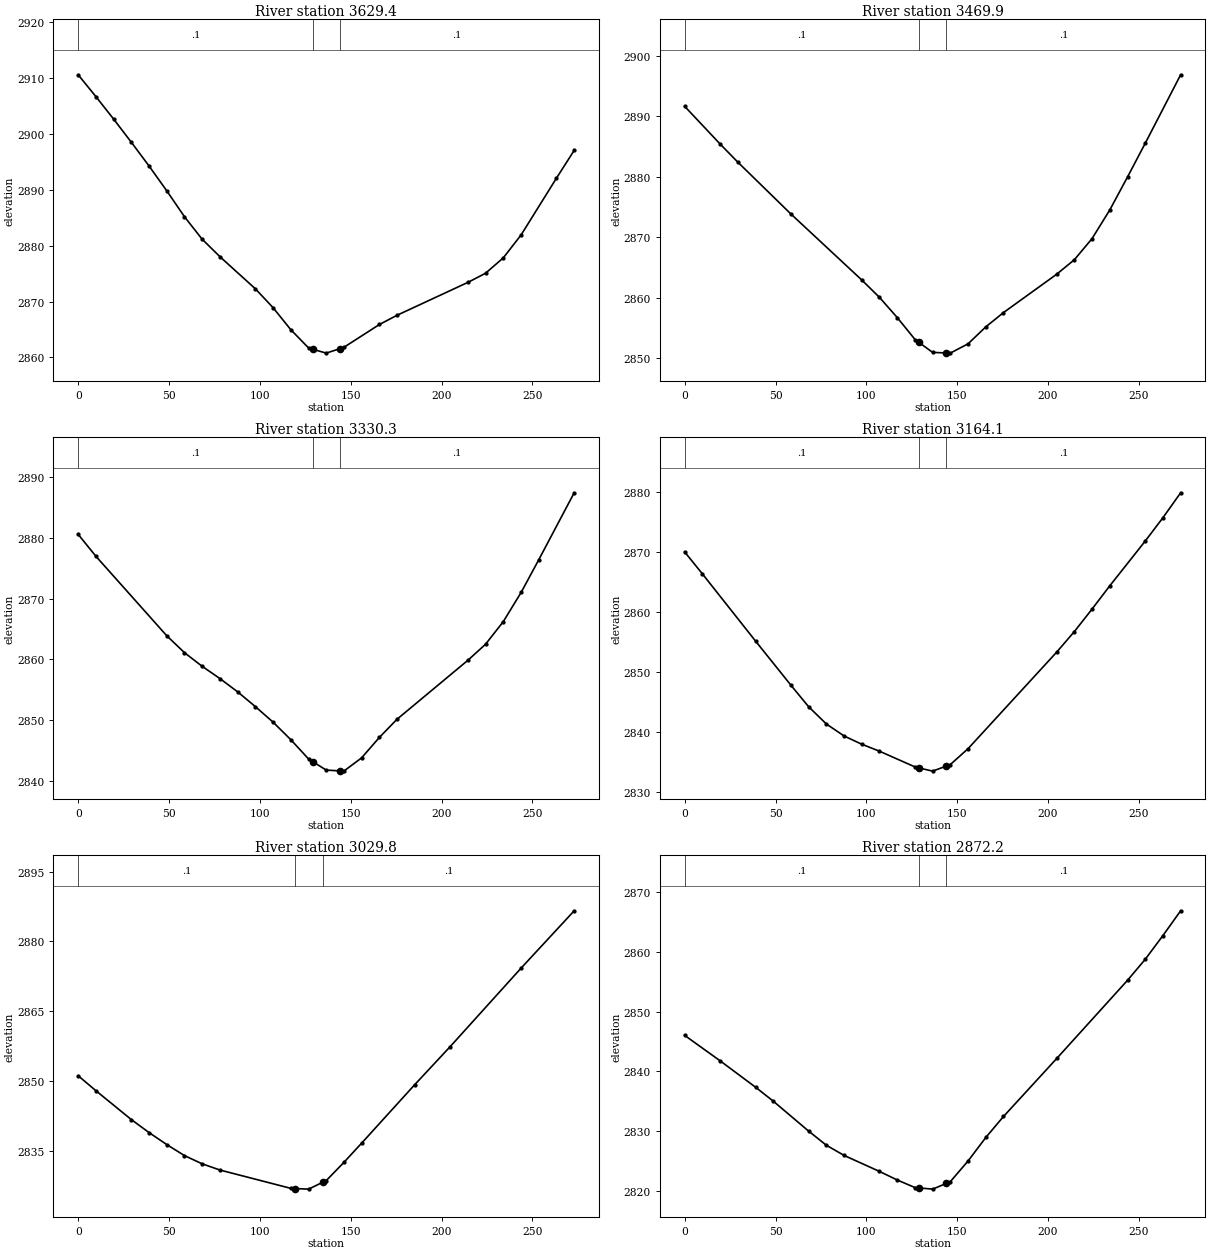
Type RM Length L Ch R = 1 ,3629.4,158.5,159.5,160.6
XS GIS Cut Line= 3
     2094686.622      409057.904     2094749.115      408936.550
     2094811.609      408815.196
#Sta/Elev= 25
       0 2910.55     9.8 2906.63    19.5 2902.63    29.2 2898.51    39.0 2894.24
    48.8 2889.78    58.5 2885.17    68.2 2881.16    78.0 2878.03    97.5 2872.29
   107.2 2868.93   117.0 2864.98   126.8 2861.71     129 2861.49   136.5 2860.78
     144 2861.57   146.2 2861.81   165.8 2865.90   175.5 2867.55   214.5 2873.43
   224.2 2875.06   234.0 2877.82   243.8 2881.92   263.2 2892.04   273.0 2897.03
#Mann= 3 , 0 , 0
       0     0.1       0     129   0.045       0     144     0.1       0
Bank Sta=     129,     144
Exp/Cntr=0.3,0.1

Type RM Length L Ch R = 1 ,3469.9,134.8,139.6,144.4
XS GIS Cut Line= 2
     2094822.797      409127.858     2094959.122      408891.332
#Sta/Elev= 22
       0 2891.63    19.5 2885.41    29.2 2882.43    58.5 2873.84    97.5 2862.94
   107.2 2860.08   117.0 2856.74   126.8 2853.11     129 2852.62   136.5 2850.98
     144 2850.89   146.2 2850.86   156.0 2852.40   165.8 2855.21   175.5 2857.56
   204.8 2863.90   214.5 2866.29   224.2 2869.76   234.0 2874.51   243.8 2879.98
   253.5 2885.52   273.0 2896.84
#Mann= 3 , 0 , 0
       0     0.1       0     129   0.045       0     144     0.1       0
Bank Sta=     129,     144
Exp/Cntr=0.3,0.1

Type RM Length L Ch R = 1 ,3330.3,164,166.2,168.4
XS GIS Cut Line= 2
     2094903.479      409203.550     2095086.161      409000.679
#Sta/Elev= 24
       0 2880.53     9.8 2876.92    48.8 2863.87    58.5 2861.11    68.2 2858.88
    78.0 2856.86    87.8 2854.67    97.5 2852.26   107.2 2849.72   117.0 2846.83
   126.8 2843.66     129 2843.24   136.5 2841.83     144 2841.70   146.2 2841.66
   156.0 2843.84   165.8 2847.20   175.5 2850.18   214.5 2859.86   224.2 2862.49
   234.0 2866.21   243.8 2871.00   253.5 2876.36   273.0 2887.36
#Mann= 3 , 0 , 0
       0     0.1       0     129   0.045       0     144     0.1       0
Bank Sta=     129,     144
Exp/Cntr=0.3,0.1

Type RM Length L Ch R = 1 ,3164.1,134.3,134.3,134.3
XS GIS Cut Line= 2
     2095019.593      409302.955     2095221.063      409118.730
#Sta/Elev= 22
       0 2870.04     9.8 2866.36    39.0 2855.16    58.5 2847.78    68.2 2844.20
    78.0 2841.31    87.8 2839.30    97.5 2837.93   107.2 2836.77   126.8 2834.14
     129 2833.97   136.5 2833.44     144 2834.28   146.2 2834.53   156.0 2837.19
   204.8 2853.32   214.5 2856.74   224.2 2860.48   234.0 2864.38   253.5 2871.85
   263.2 2875.73   273.0 2879.91
#Mann= 3 , 0 , 0
       0     0.1       0     129   0.045       0     144     0.1       0
Bank Sta=     129,     144
Exp/Cntr=0.3,0.1

Type RM Length L Ch R = 1 ,3029.8,156.8,157.6,158.4
XS GIS Cut Line= 2
     2095131.319      409380.567     2095332.789      409196.342
#Sta/Elev= 19
       0 2851.09     9.8 2847.86    29.2 2841.68    39.0 2838.87    48.8 2836.28
    58.5 2833.92    68.2 2832.16    78.0 2830.82   117.0 2826.88   119.6 2826.83
   126.8 2826.71   134.6 2828.18   136.5 2828.53   146.2 2832.44   156.0 2836.59
   185.2 2849.16   204.8 2857.38   243.8 2874.25   273.0 2886.57
#Mann= 3 , 0 , 0
       0     0.1       0   119.6   0.045       0   134.6     0.1       0
Bank Sta=   119.6,   134.6
Exp/Cntr=0.3,0.1

Type RM Length L Ch R = 1 ,2872.2,143.7,142.8,142
XS GIS Cut Line= 2
     2095234.018      409492.740     2095442.199      409316.133
#Sta/Elev= 22
       0 2846.05    19.5 2841.79    39.0 2837.37    48.8 2835.02    68.2 2830.02
    78.0 2827.64    87.8 2825.93   107.2 2823.26   117.0 2821.82   126.8 2820.55
     129 2820.49   136.5 2820.29     144 2821.24   146.2 2821.53   156.0 2825.01
   165.8 2828.96   175.5 2832.46   204.8 2842.18   243.8 2855.29   253.5 2858.79
   263.2 2862.75   273.0 2866.92
#Mann= 3 , 0 , 0
       0     0.1       0     129   0.045       0     144     0.1       0
Bank Sta=     129,     144
Exp/Cntr=0.3,0.1

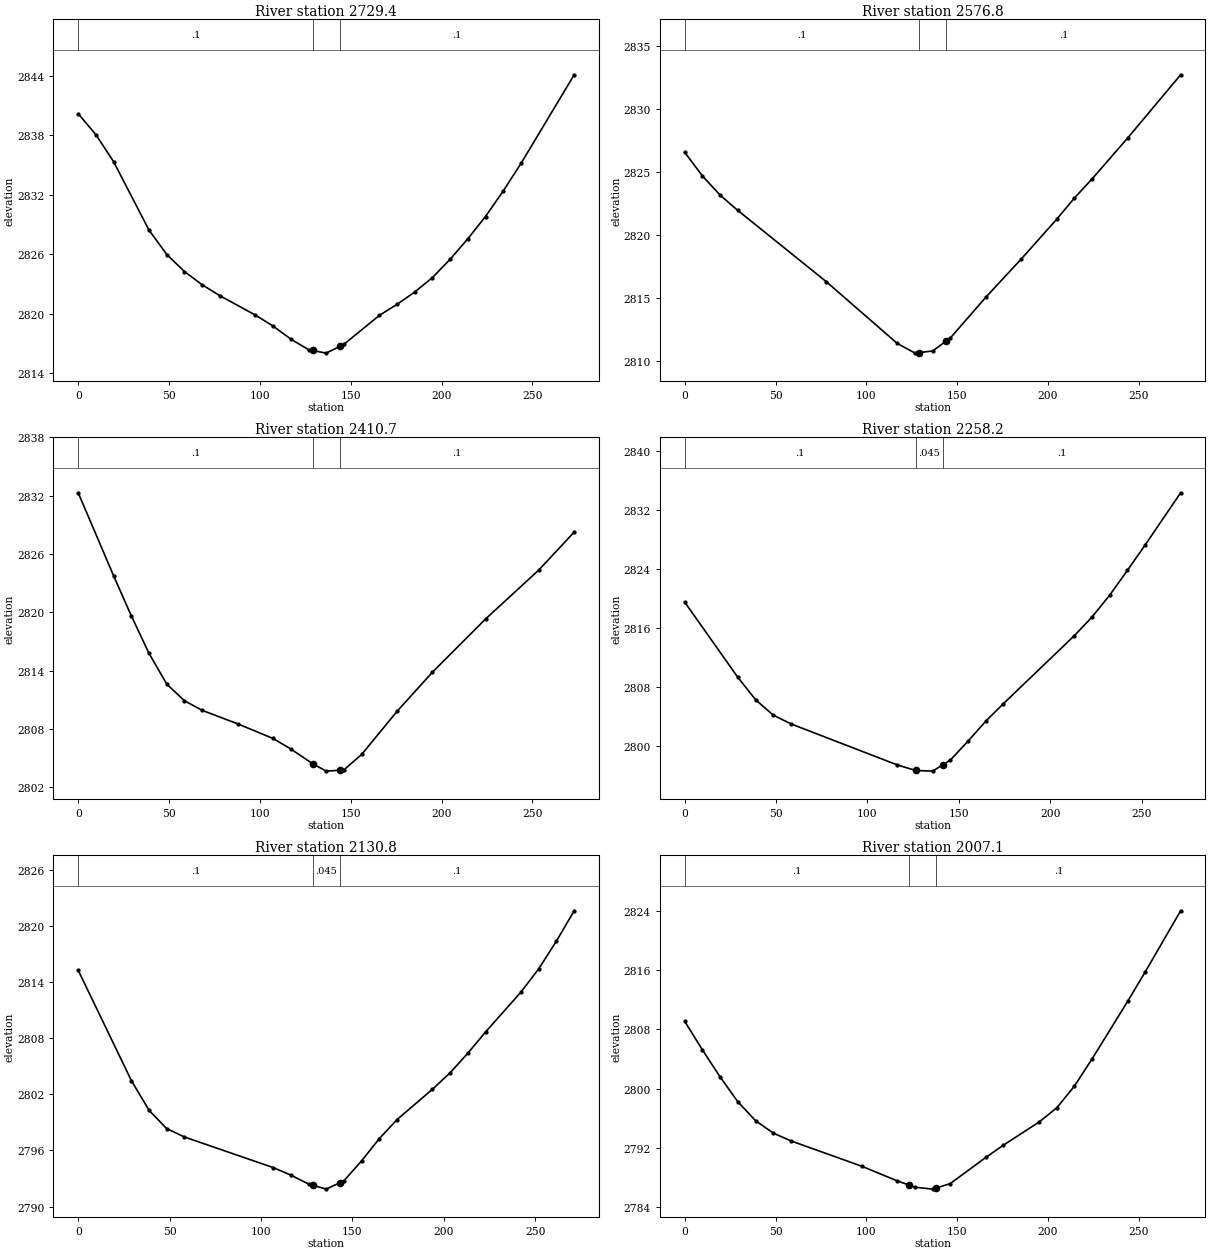
Type RM Length L Ch R = 1 ,2729.4,158.1,152.6,147.1
XS GIS Cut Line= 3
     2095333.764      409601.963     2095434.499      409509.850
     2095535.234      409417.738
#Sta/Elev= 26
       0 2840.17     9.8 2838.04    19.5 2835.32    39.0 2828.42    48.8 2825.96
    58.5 2824.25    68.2 2822.92    78.0 2821.81    97.5 2819.86   107.2 2818.76
   117.0 2817.44   126.8 2816.37     129 2816.29   136.5 2816.02     144 2816.70
   146.2 2816.90   165.8 2819.83   175.5 2820.94   185.2 2822.18   195.0 2823.64
   204.8 2825.50   214.5 2827.56   224.2 2829.80   234.0 2832.38   243.8 2835.17
   273.0 2844.09
#Mann= 3 , 0 , 0
       0     0.1       0     129   0.045       0     144     0.1       0
Bank Sta=     129,     144
Exp/Cntr=0.3,0.1

Type RM Length L Ch R = 1 ,2576.8,166.1,166.2,166.2
XS GIS Cut Line= 2
     2095468.143      409730.165     2095619.005      409502.635
#Sta/Elev= 18
       0 2826.55     9.8 2824.67    19.5 2823.16    29.2 2821.95    78.0 2816.30
   117.0 2811.42   126.8 2810.65     129 2810.69   136.5 2810.82     144 2811.61
   146.2 2811.84   165.8 2815.08   185.2 2818.09   204.8 2821.25   214.5 2822.92
   224.2 2824.43   243.8 2827.67   273.0 2832.68
#Mann= 3 , 0 , 0
       0     0.1       0     129   0.045       0     144     0.1       0
Bank Sta=     129,     144
Exp/Cntr=0.3,0.1

Type RM Length L Ch R = 1 ,2410.7,153.9,152.4,150.8
XS GIS Cut Line= 2
     2095600.209      409825.332     2095751.070      409597.802
#Sta/Elev= 20
       0 2832.28    19.5 2823.75    29.2 2819.65    39.0 2815.77    48.8 2812.61
    58.5 2810.91    68.2 2809.93    87.8 2808.54   107.2 2807.04   117.0 2805.96
     129 2804.45   136.5 2803.68     144 2803.77   146.2 2803.80   156.0 2805.39
   175.5 2809.82   195.0 2813.85   224.2 2819.31   253.5 2824.34   273.0 2828.24
#Mann= 3 , 0 , 0
       0     0.1       0     129   0.045       0     144     0.1       0
Bank Sta=     129,     144
Exp/Cntr=0.3,0.1

Type RM Length L Ch R = 1 ,2258.2,127.7,127.4,127.2
XS GIS Cut Line= 3
     2095757.481      409863.077     2095824.701      409745.242
     2095891.256      409627.035
#Sta/Elev= 19
       0 2819.52    29.1 2809.34    38.8 2806.32    48.4 2804.25    58.1 2803.06
   116.3 2797.51   126.3 2796.76   135.7 2796.67   141.3 2797.55   145.4 2798.18
   155.0 2800.72   164.7 2803.42   174.4 2805.80   213.2 2814.99   222.9 2817.52
   232.6 2820.49   242.2 2823.81   251.9 2827.24   271.3 2834.29
#Mann= 3 , 0 , 0
       0     0.1       0   126.3   0.045       0   141.3     0.1       0
Bank Sta=   126.3,   141.3
Exp/Cntr=0.3,0.1

Type RM Length L Ch R = 1 ,2130.8,122.2,123.7,125.2
XS GIS Cut Line= 3
     2095874.631      409912.024     2095941.852      409794.189
     2096008.407      409675.982
#Sta/Elev= 23
       0 2815.27    29.1 2803.47    38.8 2800.28    48.4 2798.34    58.1 2797.44
   106.6 2794.17   116.3 2793.36   126.0 2792.41   128.2 2792.28   135.7 2791.86
   143.2 2792.56   145.4 2792.76   155.0 2794.88   164.7 2797.26   174.4 2799.30
   193.8 2802.55   203.5 2804.32   213.2 2806.42   222.9 2808.69   242.2 2812.95
   251.9 2815.43   261.6 2818.40   271.3 2821.64
#Mann= 3 , 0 , 0
       0     0.1       0   128.2   0.045       0   143.2     0.1       0
Bank Sta=   128.2,   143.2
Exp/Cntr=0.3,0.1

Type RM Length L Ch R = 1 ,2007.1,132,138.2,144.9
XS GIS Cut Line= 3
     2095977.668      409963.291     2096053.090      409849.517
     2096127.869      409735.324
#Sta/Elev= 23
       0 2809.10     9.8 2805.22    19.5 2801.59    29.2 2798.25    39.0 2795.67
    48.8 2793.99    58.5 2792.94    97.5 2789.51   117.0 2787.54   123.5 2786.97
   126.8 2786.68   136.5 2786.42   138.5 2786.57   146.2 2787.17   165.8 2790.71
   175.5 2792.37   195.0 2795.47   204.8 2797.40   214.5 2800.33   224.2 2803.99
   243.8 2811.78   253.5 2815.77   273.0 2824.03
#Mann= 3 , 0 , 0
       0     0.1       0   123.5   0.045       0   138.5     0.1       0
Bank Sta=   123.5,   138.5
Exp/Cntr=0.3,0.1

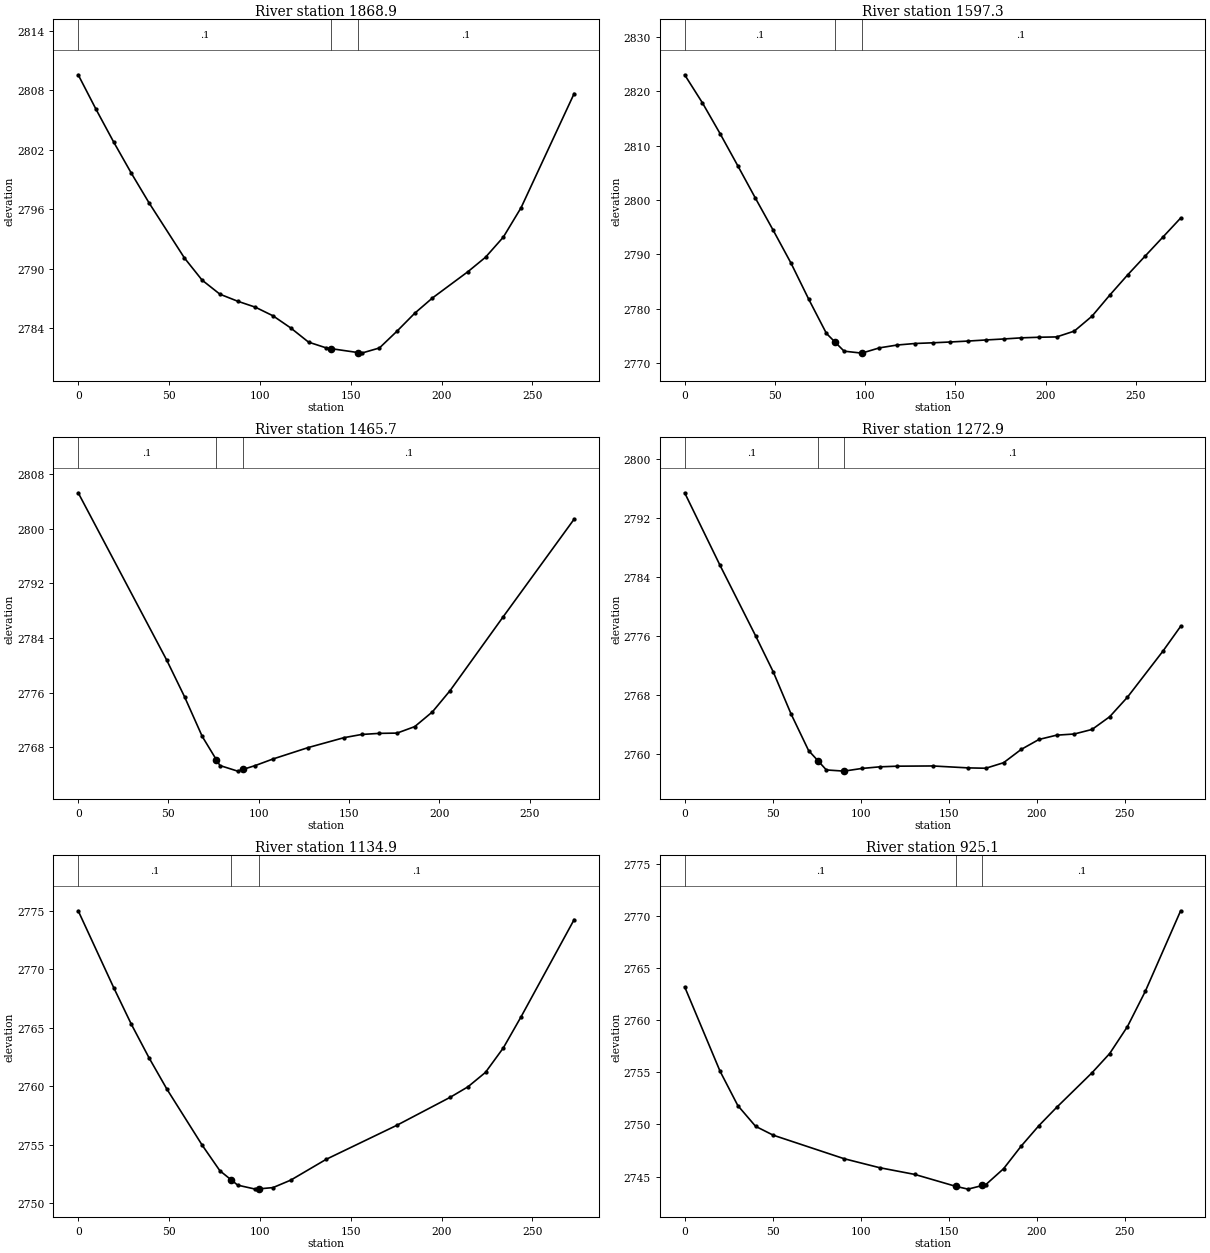
Type RM Length L Ch R = 1 ,1868.9,272.6,271.6,270.2
XS GIS Cut Line= 3
     2096054.238      410021.125     2096159.107      409933.744
     2096263.481      409845.777
#Sta/Elev= 26
       0 2809.58     9.8 2806.10    19.5 2802.80    29.2 2799.66    39.0 2796.65
    58.5 2791.08    68.2 2788.85    78.0 2787.43    87.8 2786.72    97.5 2786.12
   107.2 2785.25   117.0 2784.02   126.8 2782.59   136.5 2782.01   138.9 2781.94
   153.9 2781.54   156.0 2781.48   165.8 2782.00   175.5 2783.70   185.2 2785.50
   195.0 2787.05   214.5 2789.70   224.2 2791.16   234.0 2793.19   243.8 2796.17
   273.0 2807.69
#Mann= 3 , 0 , 0
       0     0.1       0   138.9   0.045       0   153.9     0.1       0
Bank Sta=   138.9,   153.9
Exp/Cntr=0.3,0.1

Type RM Length L Ch R = 1 ,1597.3,133.9,131.6,129.3
XS GIS Cut Line= 3
     2096224.203      410224.381     2096321.504      410127.446
     2096418.256      410029.967
#Sta/Elev= 30
       0 2823.01     9.8 2817.87    19.6 2812.20    29.4 2806.29    39.2 2800.31
    49.0 2794.44    58.9 2788.37    68.7 2781.74    78.5 2775.45    83.1 2773.91
    88.3 2772.18    98.1 2771.82   107.9 2772.79   117.7 2773.31   127.5 2773.59
   137.4 2773.72   147.2 2773.87   157.0 2774.04   166.8 2774.24   176.6 2774.42
   186.4 2774.63   196.2 2774.74   206.0 2774.80   215.8 2775.87   225.6 2778.61
   235.4 2782.47   245.3 2786.19   255.1 2789.69   264.9 2793.17   274.7 2796.66
#Mann= 3 , 0 , 0
       0     0.1       0    83.1   0.045       0    98.1     0.1       0
Bank Sta=    83.1,    98.1
Exp/Cntr=0.3,0.1

Type RM Length L Ch R = 1 ,1465.7,188.6,192.8,197
XS GIS Cut Line= 3
     2096345.113      410293.828     2096432.526      410187.889
     2096519.340      410081.464
#Sta/Elev= 20
       0 2805.27    49.0 2780.78    58.9 2775.40    68.7 2769.59    76.5 2766.19
    78.5 2765.33    88.3 2764.51    91.5 2764.78    98.1 2765.33   107.9 2766.29
   127.5 2767.97   147.2 2769.41   157.0 2769.88   166.8 2770.04   176.6 2770.08
   186.4 2771.03   196.2 2773.19   206.0 2776.31   235.4 2787.12   274.7 2801.42
#Mann= 3 , 0 , 0
       0     0.1       0    76.5   0.045       0    91.5     0.1       0
Bank Sta=    76.5,    91.5
Exp/Cntr=0.3,0.1

Type RM Length L Ch R = 1 ,1272.9,150.7,138,125.3
XS GIS Cut Line= 2
     2096467.907      410419.321     2096684.726      410239.339
#Sta/Elev= 26
       0 2795.44    20.1 2785.61    40.3 2776.07    50.3 2771.20    60.4 2765.51
    70.4 2760.53    75.8 2759.13    80.5 2757.90    90.6 2757.74    90.8 2757.75
   100.6 2758.10   110.7 2758.32   120.8 2758.41   140.9 2758.44   161.0 2758.18
   171.1 2758.13   181.2 2758.88   191.2 2760.68   201.3 2762.03   211.3 2762.61
   221.4 2762.77   231.5 2763.39   241.5 2765.11   251.6 2767.76   271.7 2773.98
   281.8 2777.35
#Mann= 3 , 0 , 0
       0     0.1       0    75.8   0.045       0    90.8     0.1       0
Bank Sta=    75.8,    90.8
Exp/Cntr=0.3,0.1

Type RM Length L Ch R = 1 ,1134.9,196.7,209.8,222.9
XS GIS Cut Line= 2
     2096620.831      410516.572     2096702.439      410256.055
#Sta/Elev= 21
       0 2775.00    19.5 2768.44    29.2 2765.31    39.0 2762.42    48.8 2759.75
    68.2 2754.96    78.0 2752.76    84.3 2751.97    87.8 2751.53    97.5 2751.19
    99.3 2751.21   107.2 2751.32   117.0 2751.96   136.5 2753.74   175.5 2756.66
   204.8 2759.05   214.5 2759.94   224.2 2761.18   234.0 2763.27   243.8 2765.94
   273.0 2774.25
#Mann= 3 , 0 , 0
       0     0.1       0    84.3   0.045       0    99.3     0.1       0
Bank Sta=    84.3,    99.3
Exp/Cntr=0.3,0.1

Type RM Length L Ch R = 1 ,925.1,210.6,214.9,219.1
XS GIS Cut Line= 2
     2096698.625      410588.961     2096919.620      410414.132
#Sta/Elev= 21
       0 2763.21    20.1 2755.11    30.2 2751.81    40.3 2749.82    50.3 2748.97
    90.6 2746.71   110.7 2745.85   130.8 2745.20   154.2 2744.05   161.0 2743.79
   169.2 2744.14   171.1 2744.22   181.2 2745.75   191.2 2747.92   201.3 2749.89
   211.3 2751.63   231.5 2754.97   241.5 2756.81   251.6 2759.40   261.7 2762.77
   281.8 2770.51
#Mann= 3 , 0 , 0
       0     0.1       0   154.2   0.045       0   169.2     0.1       0
Bank Sta=   154.2,   169.2
Exp/Cntr=0.3,0.1

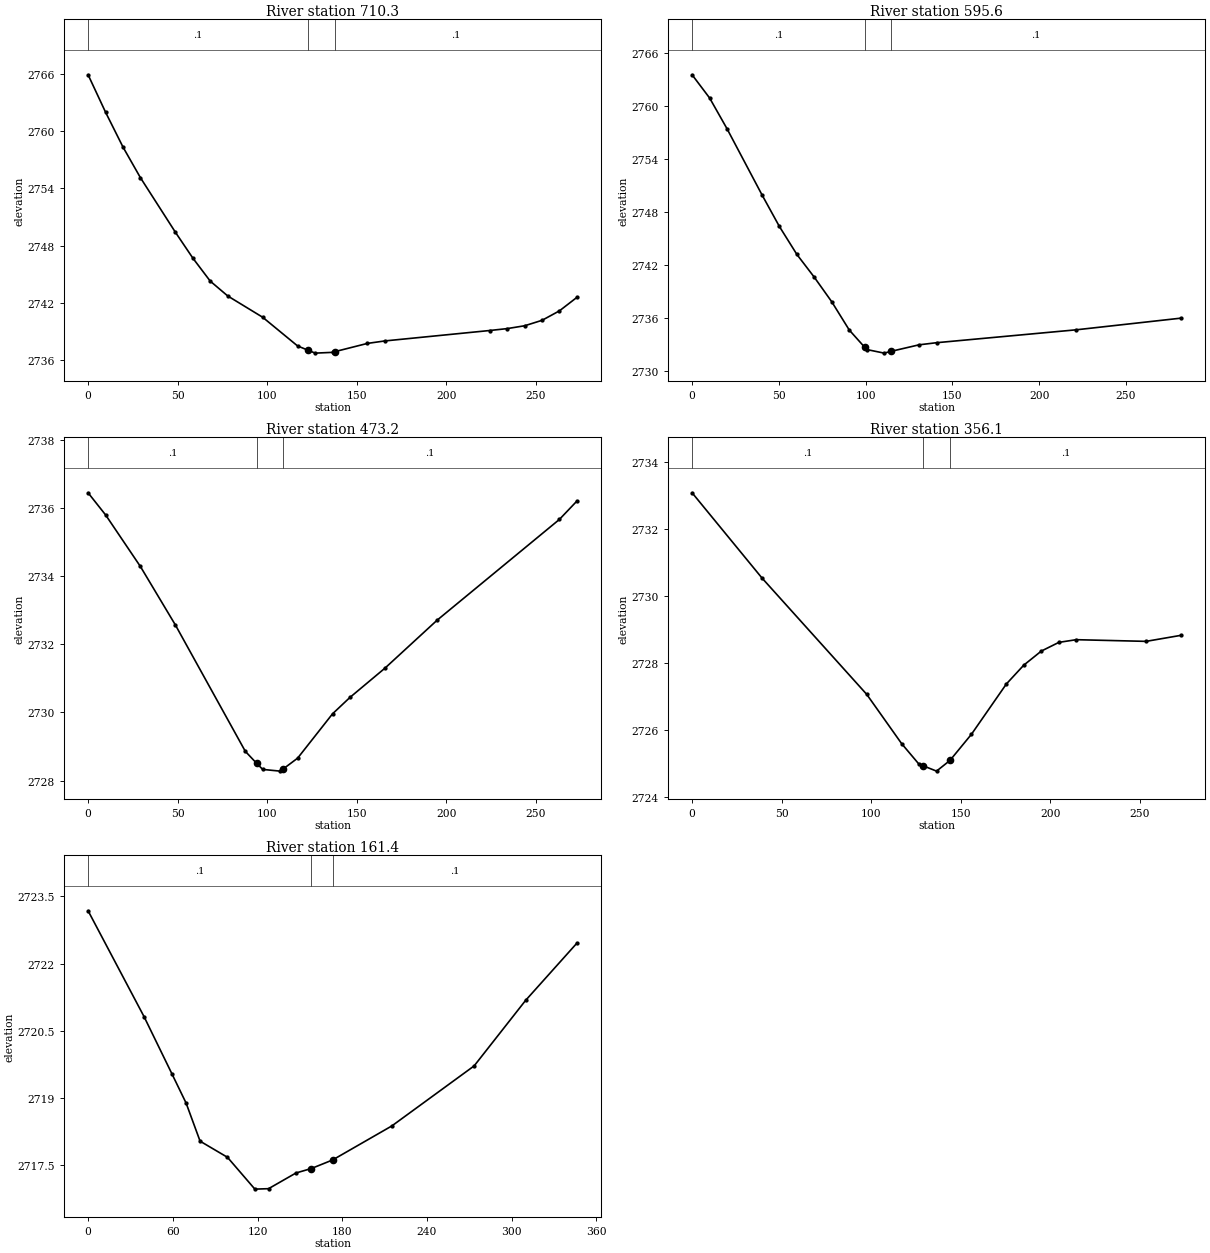
Type RM Length L Ch R = 1 ,710.3,115,114.7,114.3
XS GIS Cut Line= 3
     2096773.320      410754.814     2096893.745      410690.550
     2097014.171      410626.285
#Sta/Elev= 22
       0 2765.90     9.8 2761.96    19.5 2758.32    29.2 2755.12    48.8 2749.38
    58.5 2746.68    68.2 2744.27    78.0 2742.71    97.5 2740.48   117.0 2737.47
   122.9 2737.02   126.8 2736.72   136.5 2736.80   137.9 2736.88   156.0 2737.74
   165.8 2738.00   224.2 2739.09   234.0 2739.29   243.8 2739.59   253.5 2740.16
   263.2 2741.15   273.0 2742.57
#Mann= 3 , 0 , 0
       0     0.1       0   122.9   0.045       0   137.9     0.1       0
Bank Sta=   122.9,   137.9
Exp/Cntr=0.3,0.1

Type RM Length L Ch R = 1 ,595.6,134.9,122.4,109.9
XS GIS Cut Line= 2
     2096843.542      410848.059     2097089.340      410710.267
#Sta/Elev= 17
       0 2763.54    10.1 2760.91    20.1 2757.44    40.3 2749.94    50.3 2746.37
    60.4 2743.20    70.4 2740.63    80.5 2737.84    90.6 2734.64    99.4 2732.71
   100.6 2732.44   110.7 2732.03   114.4 2732.22   130.8 2732.97   140.9 2733.21
   221.4 2734.67   281.8 2735.99
#Mann= 3 , 0 , 0
       0     0.1       0    99.4   0.045       0   114.4     0.1       0
Bank Sta=    99.4,   114.4
Exp/Cntr=0.3,0.1

Type RM Length L Ch R = 1 ,473.2,104.6,117.1,129.5
XS GIS Cut Line= 2
     2096987.363      410953.621     2097115.689      410712.661
#Sta/Elev= 16
       0 2736.44     9.8 2735.79    29.2 2734.28    48.8 2732.56    87.8 2728.86
    94.1 2728.51    97.5 2728.33   107.2 2728.28   109.1 2728.35   117.0 2728.66
   136.5 2729.96   146.2 2730.44   165.8 2731.30   195.0 2732.71   263.2 2735.66
   273.0 2736.20
#Mann= 3 , 0 , 0
       0     0.1       0    94.1   0.045       0   109.1     0.1       0
Bank Sta=    94.1,   109.1
Exp/Cntr=0.3,0.1

Type RM Length L Ch R = 1 ,356.1,200.7,194.7,188.7
XS GIS Cut Line= 2
     2097033.193      410956.701     2097264.152      410811.143
#Sta/Elev= 16
       0 2733.08    39.0 2730.54    97.5 2727.07   117.0 2725.60   126.8 2724.98
     129 2724.94   136.5 2724.78     144 2725.10   156.0 2725.88   175.5 2727.38
   185.2 2727.94   195.0 2728.36   204.8 2728.62   214.5 2728.70   253.5 2728.65
   273.0 2728.83
#Mann= 3 , 0 , 0
       0     0.1       0     129   0.045       0     144     0.1       0
Bank Sta=     129,     144
Exp/Cntr=0.3,0.1

Type RM Length L Ch R = 1 ,161.4,154.7,161.4,168.1
XS GIS Cut Line= 4
     2097103.147      411110.303     2097182.417      411110.574
     2097319.342      410973.000     2097329.962      410900.935
#Sta/Elev= 15
       0 2723.18    39.6 2720.82    59.4 2719.54    69.4 2718.89    79.3 2718.04
    98.7 2717.68   118.1 2716.97   127.8 2716.98   147.2 2717.33   158.1 2717.43
   173.1 2717.62   215.1 2718.38   273.4 2719.72   309.8 2721.18   346.2 2722.46
#Mann= 3 , 0 , 0
       0     0.1       0   158.1   0.045       0   173.1     0.1       0
Bank Sta=   158.1,   173.1
Exp/Cntr=0.3,0.1